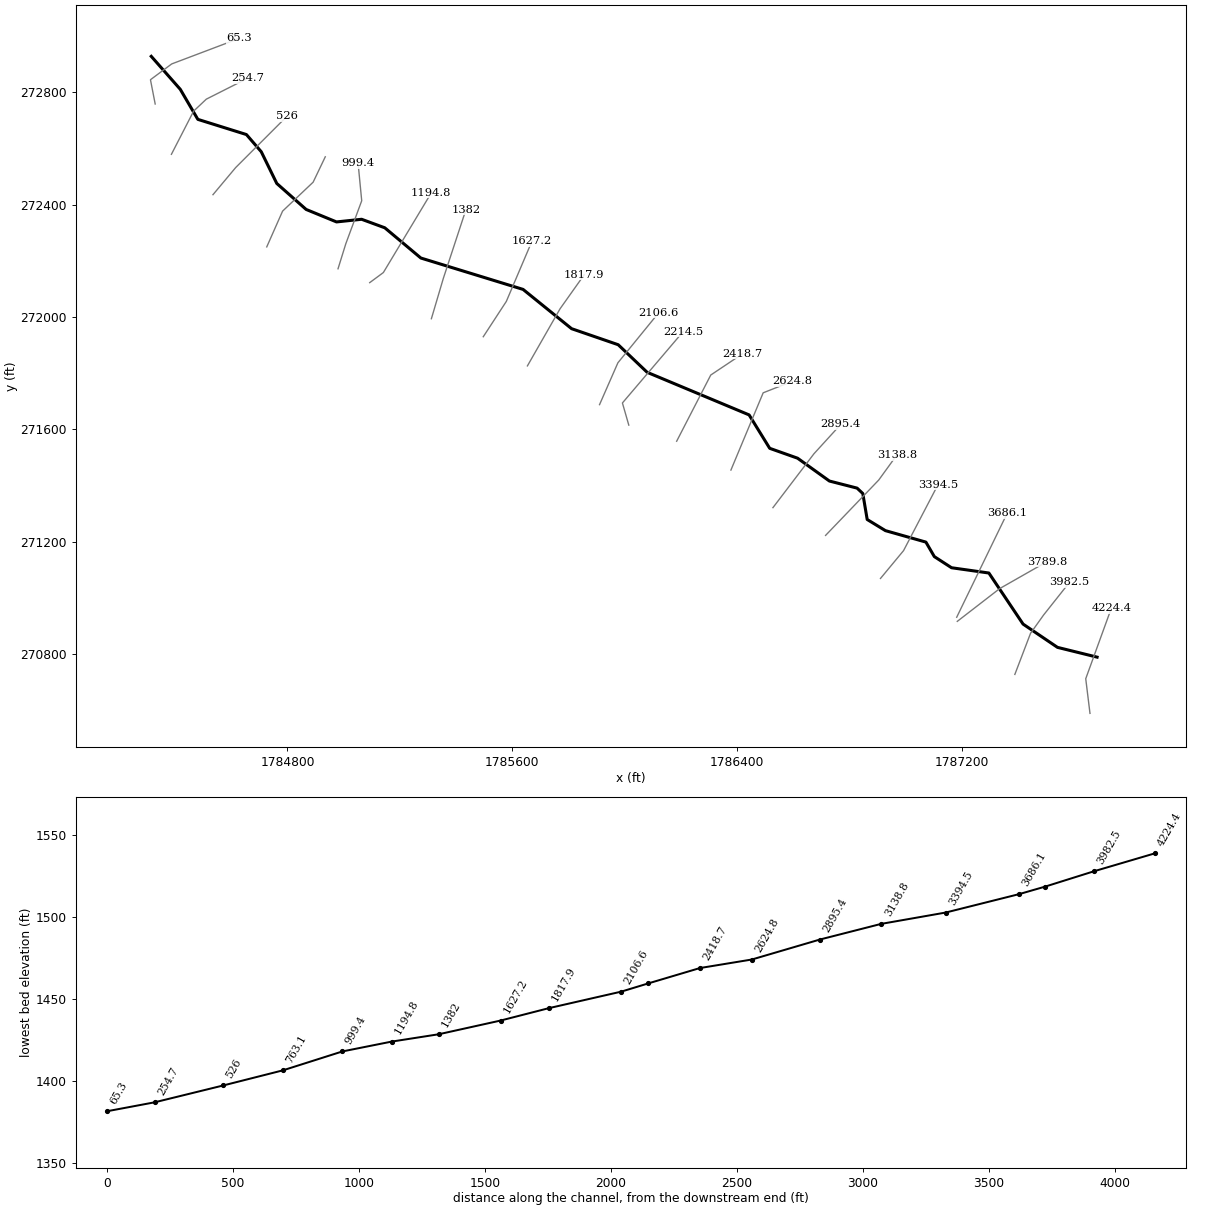
--- DingessFk.prj (project) ---

Proj Title=DingessFk
Current Plan=p01
Default Exp/Contr=0,0
English Units
Geom File=g01
Flow File=f01
Plan File=p01
BEGIN DESCRIPTION:
END DESCRIPTION:
DSS Export Rating Curves= 0
DSS Export Rating Curve Sorted= 0
DSS Export Volume Flow Curves= 0
DXF OffsetX= 0
DXF OffsetY= 0
DXF ScaleX= 0
DXF ScaleY= 0

--- DingessFk.p01 (plan) ---

Plan Title=Floodplain
Program Version=4.00
Geom File=g01
Flow File=f01
K Sum by GR=0
Std Step Tol=0.01
Critical Tol=0.01
Num of Std Step Trials=20
Max Error Tol=0.3
Flow Tol Ratio=0.001
Split Flow NTrial=30
Split Flow Tol=0.02
Split Flow Ratio=0.02
Log Output Level=0
Friction Slope Method=1
Unsteady Friction Slope Method=2
Unsteady Bridges Friction Slope Method=1
Global Log Level=0
CheckData=False
Run HTab=0
Run UNet=0
Run PostProcess=0
UNET Theta=0
UNET Theta Warmup=0
UNET ZTol=0
UNET ZSATol=0
UNET MxIter=0
UNET MaxInSteps=0
UNET DtIC=0
UNET DtMin=0
UNET MaxCRTS=0
UNET WFStab=0
UNET SFStab=0
UNET WFX=0
UNET SFX=0
UNET DSS MLevel=0
UNET DZMax Abort=0
UNET Convert EG Bridges=0
UNET Use Existing IB Tables=0
UNET Froude Limit=0
UNET Froude Power=0
Write IC File=0
Echo Input=False
Echo Output=False
Write Detailed=0

--- DingessFk.f01 (steady flow) ---

Flow Title=NFF Regression Equation
Program Version=4.00
Number of Profiles=1
Profile Names=P100yr
River Rch & RM=DingessFk,Main      ,4224.4
558.9082
River Rch & RM=DingessFk,Main      ,4224.4
1354.111
River Rch & RM=DingessFk,Main      ,3982.5
582.6630
River Rch & RM=DingessFk,Main      ,3686.1
620.0948
River Rch & RM=DingessFk,Main      ,2106.6
655.9033
River Rch & RM=DingessFk,Main      ,65.3
711.5272
Boundary for River Rch & Prof#=DingessFk,Main      ,1
Up Type=0
Dn Type=3
Dn Slope=0.035766

--- DingessFk.g01 (geometry) ---

Geom Title=USGS 10m DEM
Program Version=4.00

River Reach=DingessFk       ,Main
Reach XY= 30
     1787681.062       270789.57     1787540.106      270824.369
     1787417.654      270907.204     1787295.994      271088.925
     1787163.147      271107.688     1787101.922      271147.305
     1787071.909      271198.927     1786927.848      271239.744
     1786863.021      271279.361     1786847.415        271371.8
     1786827.006      271391.008     1786728.565      271416.218
     1786615.305      271497.464     1786516.075      271532.667
     1786442.844      271651.517     1786080.052      271803.109
     1785977.048      271901.222     1785811.117      271958.346
     1785638.506      272098.105     1785274.753      272209.752
     1785146.412      272317.354     1785064.005      272347.642
     1784974.627      272338.206     1784866.581      272382.625
     1784762.137      272475.064     1784706.914      272587.911
     1784654.092      272649.137     1784481.219       272703.16
     1784418.793      272810.005     1784315.456      272927.421

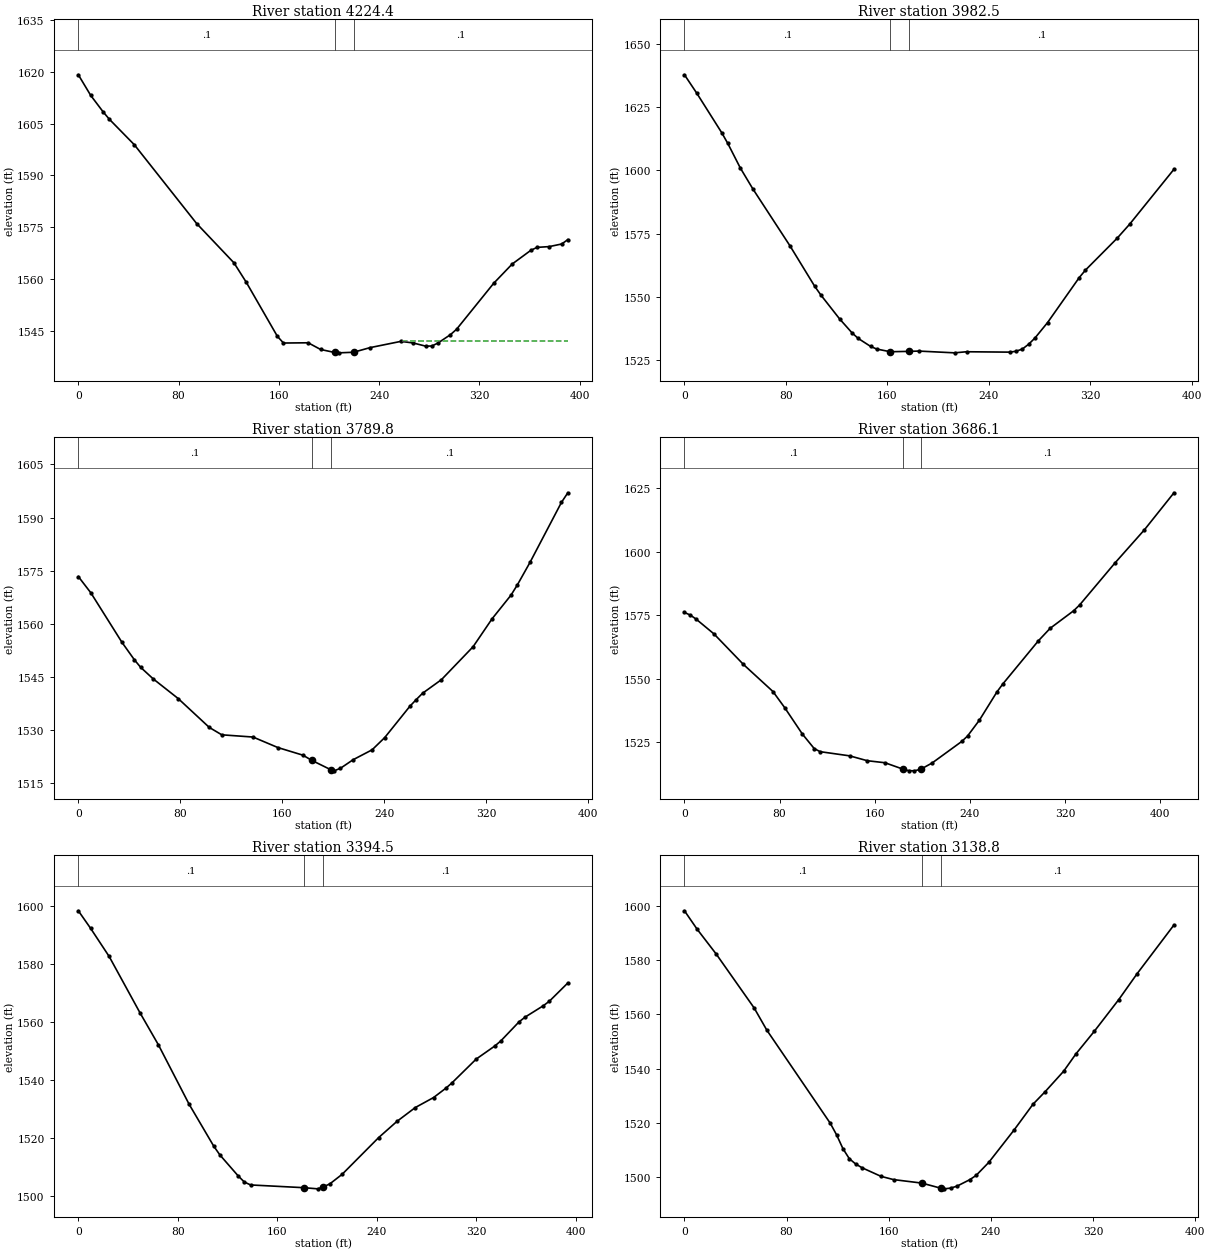
Type RM Length L Ch R = 1 ,4224.4  ,245.7,241.8,235.6
XS GIS Cut Line= 3
     1787655.771      270589.475      1787640.65        270712.8
     1787731.628      270963.183
#Sta/Elev= 30
       0 1619.14     9.9 1613.16    19.9 1608.35    24.8 1606.25    44.7 1598.88
    94.4 1576.08   124.2 1564.69   134.1 1559.02   158.8 1543.44   163.7 1541.48
   183.4 1541.55   193.3 1539.62   204.6 1538.74   208.1 1538.64   219.6 1538.81
   232.8 1540.15   257.4 1541.96   267.3 1541.49   277.2 1540.57   282.1 1540.62
     287 1541.49   296.9 1543.89   301.8 1545.46   331.4 1558.76   346.2 1564.35
     361  1568.3     366 1569.17   375.8  1569.4   385.7 1570.15   390.6 1571.42
#Mann= 3 , 0 , 0
       0      .1       0   204.6    .045       0   219.6      .1       0
#XS Ineff= 2 , 0
                          257.93         1542.03
Permanent Ineff=
       F       F
Bank Sta=204.6,219.6
XS Rating Curve= 0 ,0
Exp/Cntr=0.3,0.1

Type RM Length L Ch R = 1 ,3982.5  ,201.9,192.8,182.9
XS GIS Cut Line= 4
     1787388.419      270728.089     1787444.235      270874.335
     1787490.705      270939.523     1787583.607      271056.693
#Sta/Elev= 30
       0 1637.93     9.8 1630.56    29.4 1614.96    34.2  1610.7      44 1601.04
    53.8 1592.81    83.2 1570.15   102.7 1554.12   107.6 1550.63   122.3 1541.21
   132.1 1535.68     137 1533.45   146.8 1530.27   151.6 1529.23   162.3 1528.16
   177.3  1528.3   184.8 1528.42     213 1527.72   222.5 1528.15   256.5    1528
   261.5 1528.34   266.5 1529.22   271.5 1531.14   276.5 1533.62   286.4 1539.72
   311.4 1557.56   316.3 1560.52   341.3 1573.16   351.2 1578.74   386.1 1600.48
#Mann= 3 , 0 , 0
       0      .1       0   162.3    .045       0   177.3      .1       0
Bank Sta=162.3,177.3
XS Rating Curve= 0 ,0
Exp/Cntr=0.3,0.1

Type RM Length L Ch R = 1 ,3789.8  ,93.6,103.6,117.2
XS GIS Cut Line= 3
     1787183.585      270916.864     1787334.495       271033.53
     1787502.318      271129.122
#Sta/Elev= 30
       0 1573.32     9.8 1568.73    34.2 1554.74      44 1549.78    48.9 1547.66
    58.7 1544.41    78.3 1538.85   102.7 1530.69   112.5  1528.6     137 1527.97
   156.5    1525   176.1 1522.85   183.2 1521.36   198.2  1518.7   200.6 1518.42
   205.6 1519.15   215.5 1521.56   230.4 1524.36   240.3 1527.82   260.1  1536.7
     265 1538.55     270 1540.35   284.8 1544.19   309.6 1553.49   324.5 1561.39
   339.3 1568.05   344.3 1570.95   354.2  1577.3   378.9 1594.28   383.9 1596.99
#Mann= 3 , 0 , 0
       0      .1       0   183.2    .045       0   198.2      .1       0
Bank Sta=183.2,198.2
XS Rating Curve= 0 ,0
Exp/Cntr=0.3,0.1

Type RM Length L Ch R = 1 ,3686.1  ,291.4,291.6,291.6
XS GIS Cut Line= 2
     1787181.511       270931.55     1787361.261      271301.835
#Sta/Elev= 30
       0 1576.07       5 1575.01     9.9 1573.41    24.8 1567.64    49.6 1555.63
    74.4    1545    84.3 1538.64    99.2 1528.25   109.1 1522.58   114.1 1521.36
   138.9 1519.72   153.7 1517.81   168.6 1517.01   183.9 1514.47   188.4 1513.91
   193.4 1513.83   198.9 1514.51   208.3 1516.93   233.1 1525.36     238 1527.49
     248 1533.74   262.8 1544.88   267.8 1548.03   297.6 1564.93   307.5 1569.84
   327.3 1576.75   332.3 1579.02     362 1595.51   386.8 1608.57   411.6 1623.09
#Mann= 3 , 0 , 0
       0      .1       0   183.9    .045       0   198.9      .1       0
Bank Sta=183.9,198.9
XS Rating Curve= 0 ,0
Exp/Cntr=0.3,0.1

Type RM Length L Ch R = 1 ,3394.5  ,260,255.8,251.1
XS GIS Cut Line= 3
     1786910.289       271069.52     1786992.439      271168.647
      1787115.07      271403.581
#Sta/Elev= 30
       0 1598.33     9.9 1592.27    24.8  1582.6    49.5 1563.29    64.4  1552.2
    89.1 1531.75   108.9 1517.33   113.9 1514.27   128.7 1507.01   133.6 1504.94
   138.6 1503.95   181.7    1503   192.5 1502.61   196.7 1503.19   202.4 1504.34
   212.2  1507.6   241.6 1520.25   256.3 1525.82   271.1  1530.6   285.8 1534.04
   295.6 1537.23   300.5 1539.05   320.1 1547.29   334.9 1551.73   339.8 1553.49
   354.5 1560.07   359.4 1561.72   374.1 1565.65     379 1567.22   393.8 1573.48
#Mann= 3 , 0 , 0
       0      .1       0   181.7    .045       0   196.7      .1       0
Bank Sta=181.7,196.7
XS Rating Curve= 0 ,0
Exp/Cntr=0.3,0.1

Type RM Length L Ch R = 1 ,3138.8  ,243.1,243.3,244
XS GIS Cut Line= 3
     1786714.938      271222.729     1786904.016      271419.717
     1786968.786      271509.059
#Sta/Elev= 30
       0 1598.17     9.9 1591.39    24.8 1582.27    54.6 1562.35    64.5 1554.19
   114.2 1519.88   119.2 1515.56   124.1 1510.53   129.1 1506.83     134  1504.9
     139  1503.5   153.9 1500.32   163.8 1499.11   185.9 1497.83   200.9 1495.93
   203.5 1495.71   208.5 1495.98   213.5 1496.71   223.4 1499.07   228.4 1500.64
   238.3 1505.43   258.2 1517.41     273 1526.89   282.6 1531.56     297 1539.05
   306.6 1545.43     321 1553.76   340.2 1565.47   354.6 1575.03   383.4 1592.94
#Mann= 3 , 0 , 0
       0      .1       0   185.9    .045       0   200.9      .1       0
Bank Sta=185.9,200.9
XS Rating Curve= 0 ,0
Exp/Cntr=0.3,0.1

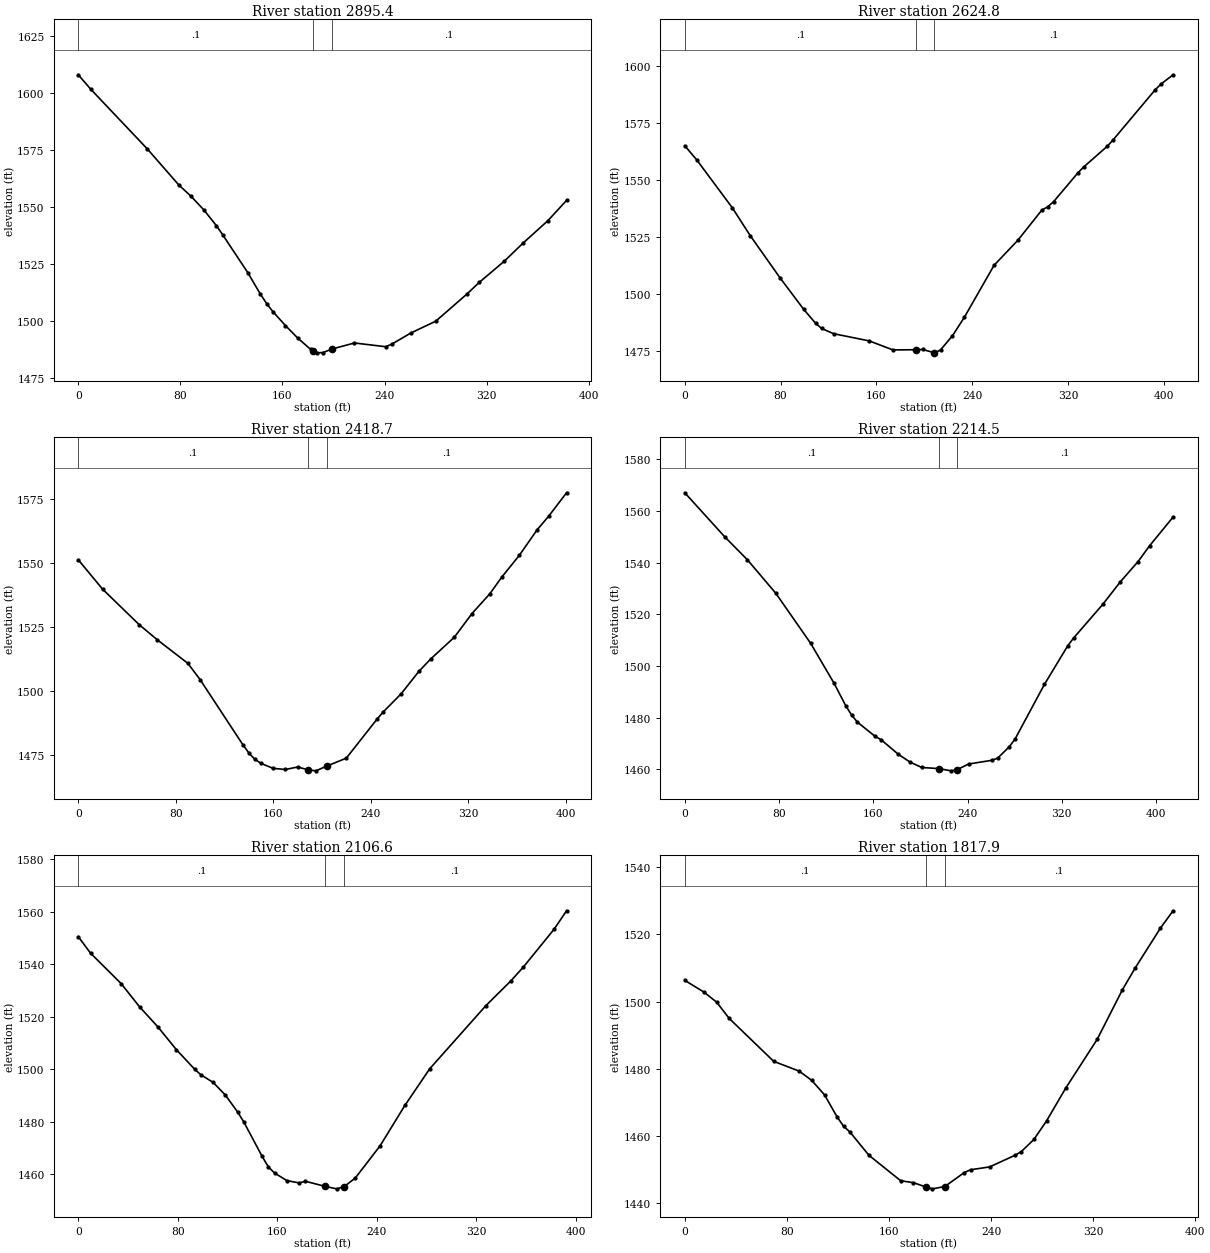
Type RM Length L Ch R = 1 ,2895.4  ,264.8,270.6,276.5
XS GIS Cut Line= 3
     1786527.641      271321.538     1786673.601      271513.303
     1786769.069      271617.888
#Sta/Elev= 30
       0 1607.82     9.8 1601.49    54.1 1575.39    78.7 1559.66    88.5  1554.6
    98.4  1548.7   108.2 1541.84   113.1 1537.89   132.8 1521.28   142.6 1511.96
   147.6 1507.74   152.5  1504.2   162.3 1498.13   172.1 1492.57     182 1487.73
   183.8 1487.15   186.9 1486.18   191.8  1486.3   198.8 1487.85   216.4 1490.49
     241 1488.85   245.9 1490.05   260.5 1494.83   280.1 1500.02   304.5 1511.89
   314.2    1517   333.8 1526.26   348.4 1534.12     368 1544.02   382.6 1552.87
#Mann= 3 , 0 , 0
       0      .1       0   183.8    .045       0   198.8      .1       0
Bank Sta=183.8,198.8
XS Rating Curve= 0 ,0
Exp/Cntr=0.3,0.1

Type RM Length L Ch R = 1 ,2624.8  ,208,206.1,204.2
XS GIS Cut Line= 3
     1786378.106      271455.199     1786492.882      271730.165
      1786595.01      271770.431
#Sta/Elev= 30
       0 1564.95     9.9 1558.79    39.7 1537.68    54.6  1525.5    79.5 1506.94
    99.3 1493.08   109.2 1486.98   114.2 1484.72   124.2  1482.4     154 1479.23
   173.8 1475.27   193.3 1475.36   198.6 1475.46   208.3 1474.03   208.6 1473.99
   213.5 1475.26   223.5 1481.51   233.4 1489.59   258.2 1512.42   278.1 1523.45
     298 1536.62     303 1538.14   307.9 1540.37   327.9 1552.84   332.9 1555.56
   352.8 1564.75   357.8 1567.64   392.8 1589.56   397.8 1592.13   407.7 1596.12
#Mann= 3 , 0 , 0
       0      .1       0   193.3    .045       0   208.3      .1       0
Bank Sta=193.3,208.3
XS Rating Curve= 0 ,0
Exp/Cntr=0.3,0.1

Type RM Length L Ch R = 1 ,2418.7  ,209.7,204.3,198.7
XS GIS Cut Line= 3
     1786185.016      271557.837     1786306.355      271793.416
     1786419.311       271868.89
#Sta/Elev= 30
       0 1551.35      20 1539.84      50 1525.97      65 1520.01      90 1510.82
     100 1504.49     135 1479.08     140 1475.81     145 1473.29     150 1471.69
     160 1469.76     170 1469.32     180 1470.28   188.8 1469.19     195 1468.79
   203.8 1470.61     220 1473.75     245 1488.88     250 1491.68     265 1498.91
   279.6 1507.71   289.2 1512.51   308.7 1521.07   323.2 1530.33   337.8 1538.04
   347.5 1544.49     362 1553.07   376.6 1563.04   386.3 1568.52   400.8 1577.56
#Mann= 3 , 0 , 0
       0      .1       0   188.8    .045       0   203.8      .1       0
Bank Sta=188.8,203.8
XS Rating Curve= 0 ,0
Exp/Cntr=0.3,0.1

Type RM Length L Ch R = 1 ,2214.5  ,106.4,107.8,109
XS GIS Cut Line= 3
      1786014.68      271615.188     1785992.035      271694.021
     1786207.463      271947.093
#Sta/Elev= 30
       0 1567.11    33.8  1550.1    53.1 1541.19    77.2 1528.22   106.8 1508.84
   126.7 1493.36   136.6 1484.67   141.6 1481.02   146.5 1478.33   161.4 1472.85
   166.4 1471.57   181.2 1465.89   191.2 1462.85   201.1 1460.77   215.9 1460.33
   225.9 1459.47   230.9 1459.87   240.8  1462.1   260.6 1463.55   265.6 1464.42
   275.5 1468.84   280.4 1471.88   305.2 1492.93   325.1 1507.95     330  1510.9
   354.8 1523.96   369.7 1532.67   384.6 1540.45   394.5 1546.62   414.4 1557.71
#Mann= 3 , 0 , 0
       0      .1       0   215.9    .045       0   230.9      .1       0
Bank Sta=215.9,230.9
XS Rating Curve= 0 ,0
Exp/Cntr=0.3,0.1

Type RM Length L Ch R = 1 ,2106.6  ,285.9,288.8,291.9
XS GIS Cut Line= 3
      1785910.61       271688.02     1785975.929      271836.941
     1786121.149      272015.078
#Sta/Elev= 30
       0 1550.54     9.9 1544.23    34.5 1532.64    49.3 1523.78    64.1 1516.09
    78.8  1507.5    93.6 1499.98    98.6 1497.88   108.4 1494.99   118.3 1490.12
   128.1 1483.69     133 1479.95   147.8 1466.76   152.8 1462.78   157.7 1460.48
   167.6 1457.58   177.6 1456.68   182.6  1457.3   198.5 1455.36   207.6 1454.43
   213.5 1455.22   222.6 1458.54   242.6 1470.86   262.5 1486.24   282.5 1500.23
   327.5 1524.22   347.5 1533.62   357.5 1538.86   382.4 1553.39   392.4 1560.41
#Mann= 3 , 0 , 0
       0      .1       0   198.5    .045       0   213.5      .1       0
Bank Sta=198.5,213.5
XS Rating Curve= 0 ,0
Exp/Cntr=0.3,0.1

Type RM Length L Ch R = 1 ,1817.9  ,187.9,190.6,193.4
XS GIS Cut Line= 3
     1785653.968      271825.905     1785770.009      272028.996
     1785856.134      272150.325
#Sta/Elev= 30
       0 1506.33    14.9 1502.86    24.9 1499.87    34.8    1495    69.7 1482.23
    89.6 1479.34    99.5 1476.57   109.5 1472.28   119.4 1465.68   124.4 1462.95
   129.4 1461.23   144.3 1454.29   169.2 1446.72   179.2 1446.15   188.8 1444.88
   194.1 1444.31   203.8    1445     219 1449.14     224 1449.99   238.9 1450.83
   258.7 1454.28   263.7 1455.37   273.6    1459   283.5  1464.5   298.4 1474.18
   323.2 1488.78     343 1503.54   352.9 1509.96   372.8 1521.89   382.7 1527.03
#Mann= 3 , 0 , 0
       0      .1       0   188.8    .045       0   203.8      .1       0
Bank Sta=188.8,203.8
XS Rating Curve= 0 ,0
Exp/Cntr=0.3,0.1

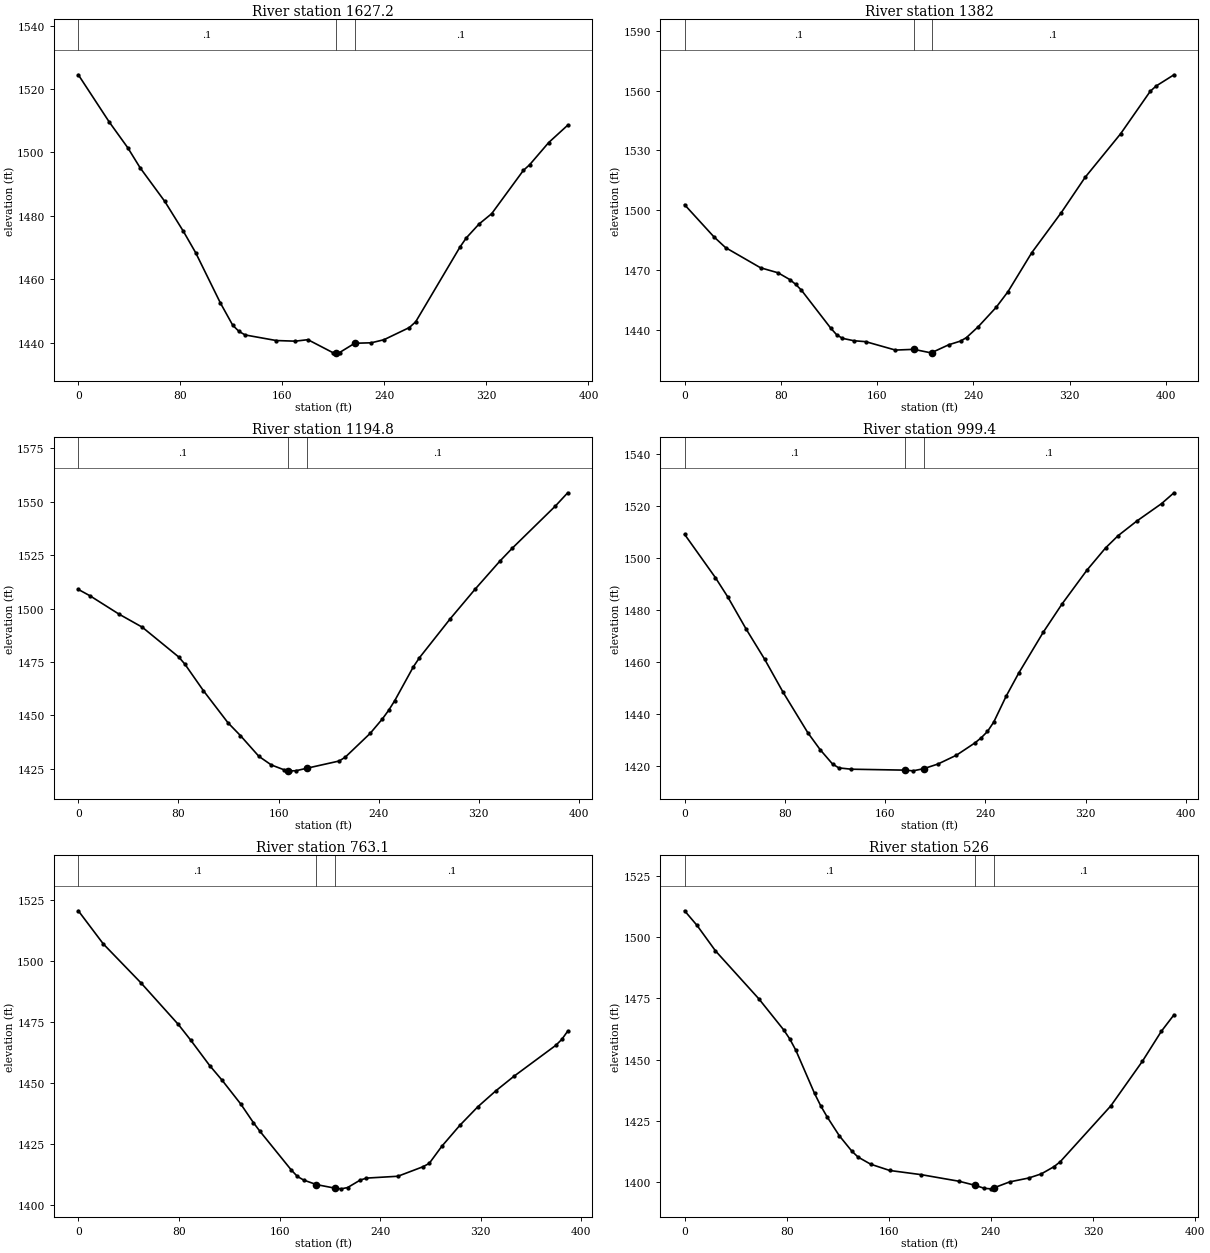
Type RM Length L Ch R = 1 ,1627.2  ,243.4,245.3,247.1
XS GIS Cut Line= 3
     1785496.909      271929.676     1785578.964      272055.458
     1785670.427      272270.338
#Sta/Elev= 30
       0 1524.49    24.2 1509.62    38.8 1501.46    48.4 1495.19    67.8 1484.55
    82.4  1475.1      92 1468.38   111.4 1452.52   121.1 1445.48     126 1443.55
   130.8 1442.44   155.2 1440.68   170.1 1440.48     180 1440.95   199.9  1436.8
   201.7 1436.83   204.8 1436.89   216.7 1439.82   229.7 1439.97   239.6 1440.93
   259.5 1444.77   264.5 1446.58   299.2 1470.14   304.2 1473.05   314.2 1477.43
   324.1 1480.69   348.9 1494.31   353.9 1496.14   368.8 1503.12   383.7 1508.59
#Mann= 3 , 0 , 0
       0      .1       0   201.7    .045       0   216.7      .1       0
Bank Sta=201.7,216.7
XS Rating Curve= 0 ,0
Exp/Cntr=0.3,0.1

Type RM Length L Ch R = 1 ,1382    ,192.2,187.1,182.1
XS GIS Cut Line= 3
     1785312.261      271993.731     1785355.003      272138.072
     1785435.035      272381.396
#Sta/Elev= 30
       0 1502.77    24.3 1486.71      34 1481.27    63.1 1471.14    77.7 1468.61
    87.4 1465.23    92.3 1462.83    97.1 1459.89   121.4 1440.89   126.3 1437.58
   131.1 1435.75   140.8 1434.52   150.5 1434.07   175.2 1429.85   190.5 1430.21
   204.7 1428.46   205.5 1428.61   219.5  1432.5   229.4 1434.38   234.3 1436.14
   244.1  1441.6   258.9 1451.27   268.8 1459.18   288.5 1478.69   313.1 1498.86
   332.8 1516.46   362.4  1538.4     387 1559.69   391.9 1562.34   406.7 1567.96
#Mann= 3 , 0 , 0
       0      .1       0   190.5    .045       0   205.5      .1       0
Bank Sta=190.5,205.5
XS Rating Curve= 0 ,0
Exp/Cntr=0.3,0.1

Type RM Length L Ch R = 1 ,1194.8  ,191.8,195.4,199.2
XS GIS Cut Line= 3
     1785092.786      272122.142     1785141.368       272158.08
     1785311.759       272441.42
#Sta/Elev= 30
       0 1508.95     9.3 1505.97    32.5 1497.38    51.1 1491.26    80.2 1477.32
    85.1    1474    99.9 1461.58   119.6 1446.49   129.5 1440.52   144.3 1430.77
   154.2 1426.75   164.1 1424.54   167.8 1424.12     169 1423.98   173.9 1424.02
   182.8 1425.22   208.5 1428.59   213.4 1430.42   233.2  1441.5     243  1448.3
     248 1452.32   252.9 1456.88   267.7 1472.65   272.6 1476.94   297.3 1495.26
     317 1508.99   336.8 1522.14   346.6 1528.14   381.2 1547.97   391.1 1554.21
#Mann= 3 , 0 , 0
       0      .1       0   167.8    .045       0   182.8      .1       0
Bank Sta=167.8,182.8
XS Rating Curve= 0 ,0
Exp/Cntr=0.3,0.1

Type RM Length L Ch R = 1 ,999.4   ,245.8,236.3,226.7
XS GIS Cut Line= 4
     1784980.059      272171.437     1785007.742      272260.571
     1785064.347       272413.56     1785051.467      272546.907
#Sta/Elev= 30
       0 1509.05    24.6 1492.37    34.4 1484.99    49.1 1472.57    63.9 1460.93
    78.6 1448.23    98.3 1432.67   108.2 1426.11     118 1420.63     123 1419.13
   132.9 1418.62   175.8 1418.26   182.3 1417.99   190.8 1418.83   202.1 1420.61
   216.9 1424.02   231.7 1428.77   236.7 1430.75   241.6 1433.14   246.6 1436.74
   256.5 1446.71   266.4  1455.5   286.2 1471.42   301.1 1482.23     321 1495.28
   335.8  1503.8   345.8 1508.52   360.7 1514.15   380.5 1520.88   390.4 1525.05
#Mann= 3 , 0 , 0
       0      .1       0   175.8    .045       0   190.8      .1       0
Bank Sta=175.8,190.8
XS Rating Curve= 0 ,0
Exp/Cntr=0.3,0.1

Type RM Length L Ch R = 1 ,763.1   ,236.6,237.1,237.6
XS GIS Cut Line= 4
     1784726.433      272249.326     1784782.776      272376.614
     1784891.525      272479.681     1784934.715      272569.977
#Sta/Elev= 30
       0 1520.68    19.9 1507.04    49.7 1491.13    79.5    1474    89.5 1467.45
   104.4 1457.13   114.3 1451.09   129.3  1441.2   139.2 1433.66   144.2 1430.24
   169.2 1414.28   174.2 1411.55   179.2 1410.07   189.3 1408.22   204.3 1406.72
   209.1 1406.47   214.1    1407   224.1 1410.06   229.1 1410.88   254.1 1411.64
     274 1415.54     279 1416.92     289 1423.95   303.3 1432.53   317.6 1440.16
   331.9 1446.71   346.2 1452.64   379.6  1465.4   384.4 1467.85   389.1 1471.25
#Mann= 3 , 0 , 0
       0      .1       0   189.3    .045       0   204.3      .1       0
Bank Sta=189.3,204.3
XS Rating Curve= 0 ,0
Exp/Cntr=0.3,0.1

Type RM Length L Ch R = 1 ,526     ,264,271.4,274.5
XS GIS Cut Line= 3
     1784535.091      272435.147     1784615.994       272531.78
     1784798.003      272713.789
#Sta/Elev= 30
       0  1510.8     9.7 1504.86    24.2 1494.43    58.2 1474.83    77.6 1462.19
    82.4 1458.47    87.2  1453.8   101.8 1436.23   106.6 1431.21   111.5 1426.78
   121.2 1418.94     131 1412.66   135.9 1410.22   145.8 1407.31   160.7 1404.75
   185.4 1403.04   215.1 1400.34   227.4 1398.71   234.9 1397.45   239.9 1397.25
   242.4 1397.67   254.7 1400.09   269.6 1401.67   279.5 1403.37   289.4  1406.3
   294.3 1408.32   333.9 1431.12   358.7 1449.37   373.5 1461.58   383.4 1468.31
#Mann= 3 , 0 , 0
       0      .1       0   227.4    .045       0   242.4      .1       0
Bank Sta=227.4,242.4
XS Rating Curve= 0 ,0
Exp/Cntr=0.3,0.1

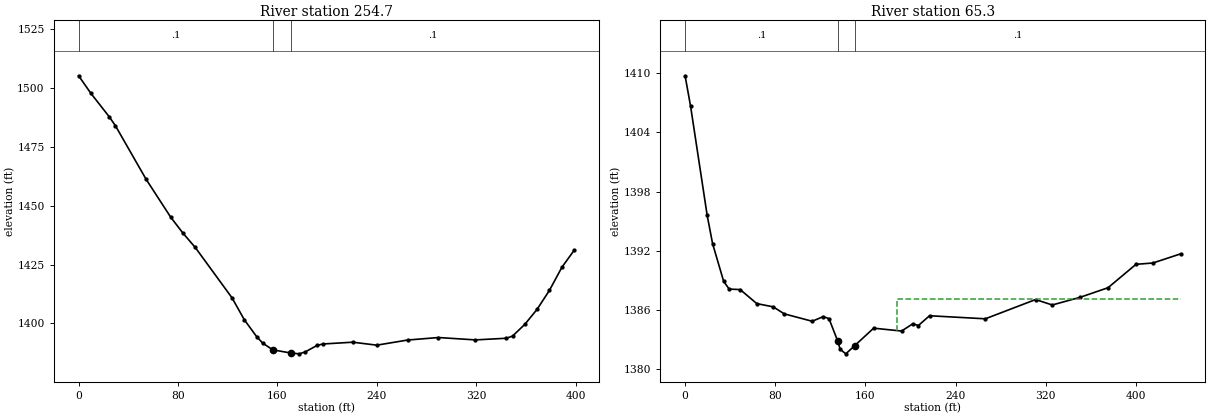
Type RM Length L Ch R = 1 ,254.7   ,200.1,189.4,182.9
XS GIS Cut Line= 4
     1784387.208      272578.817     1784466.256      272732.506
     1784511.436      272775.104     1784657.632      272848.919
#Sta/Elev= 30
       0 1505.31     9.9 1497.81    24.7 1487.83    29.6 1484.06    54.3 1461.27
    74.1 1445.14    83.9 1438.39    93.8  1432.3   123.4 1410.85   133.3 1401.53
   143.2 1394.36   148.1 1391.58   156.2 1388.72   171.2 1387.33   177.6 1387.02
   182.4 1387.86   191.9 1390.62   196.7 1391.22   220.6 1391.97   239.9 1390.71
   264.7 1392.89   289.5 1393.96   319.3 1392.95   344.1 1393.65   349.1 1394.57
     359 1399.57   368.9 1405.99   378.8 1414.02   388.8 1423.83   398.7 1431.09
#Mann= 3 , 0 , 0
       0      .1       0   156.2    .045       0   171.2      .1       0
Bank Sta=156.2,171.2
XS Rating Curve= 0 ,0
Exp/Cntr=0.3,0.1

Type RM Length L Ch R = 1 ,65.3    ,61.9,65.3,68.7
XS GIS Cut Line= 4
     1784329.479       272757.81     1784312.623      272844.202
     1784388.197      272900.412     1784629.062      272991.485
#Sta/Elev= 30
       0 1409.73     4.9 1406.62    19.6 1395.58    24.4 1392.72    34.2 1388.91
    39.1 1388.12    48.9 1388.07    63.6 1386.65    78.2 1386.32      88 1385.61
   112.8 1384.86   122.7 1385.34   127.7 1385.12   135.5 1382.83   137.6 1382.02
   142.6 1381.56   150.5 1382.39   167.3 1384.16   192.1 1383.87     202  1384.6
     207 1384.43   216.9 1385.42   266.4 1385.11     311 1387.06   325.8 1386.51
   350.6 1387.29   375.3 1388.26   400.1 1390.63     415 1390.76   439.7 1391.69
#Mann= 3 , 0 , 0
       0      .1       0   135.5    .045       0   150.5      .1       0
#XS Ineff= 2 , 0
                          187.78         1387.12
Permanent Ineff=
       F       F
Bank Sta=135.5,150.5
XS Rating Curve= 0 ,0
Exp/Cntr=0.3,0.1

Chan Stop Cuts=-1
Use User Specified Reach Order=0